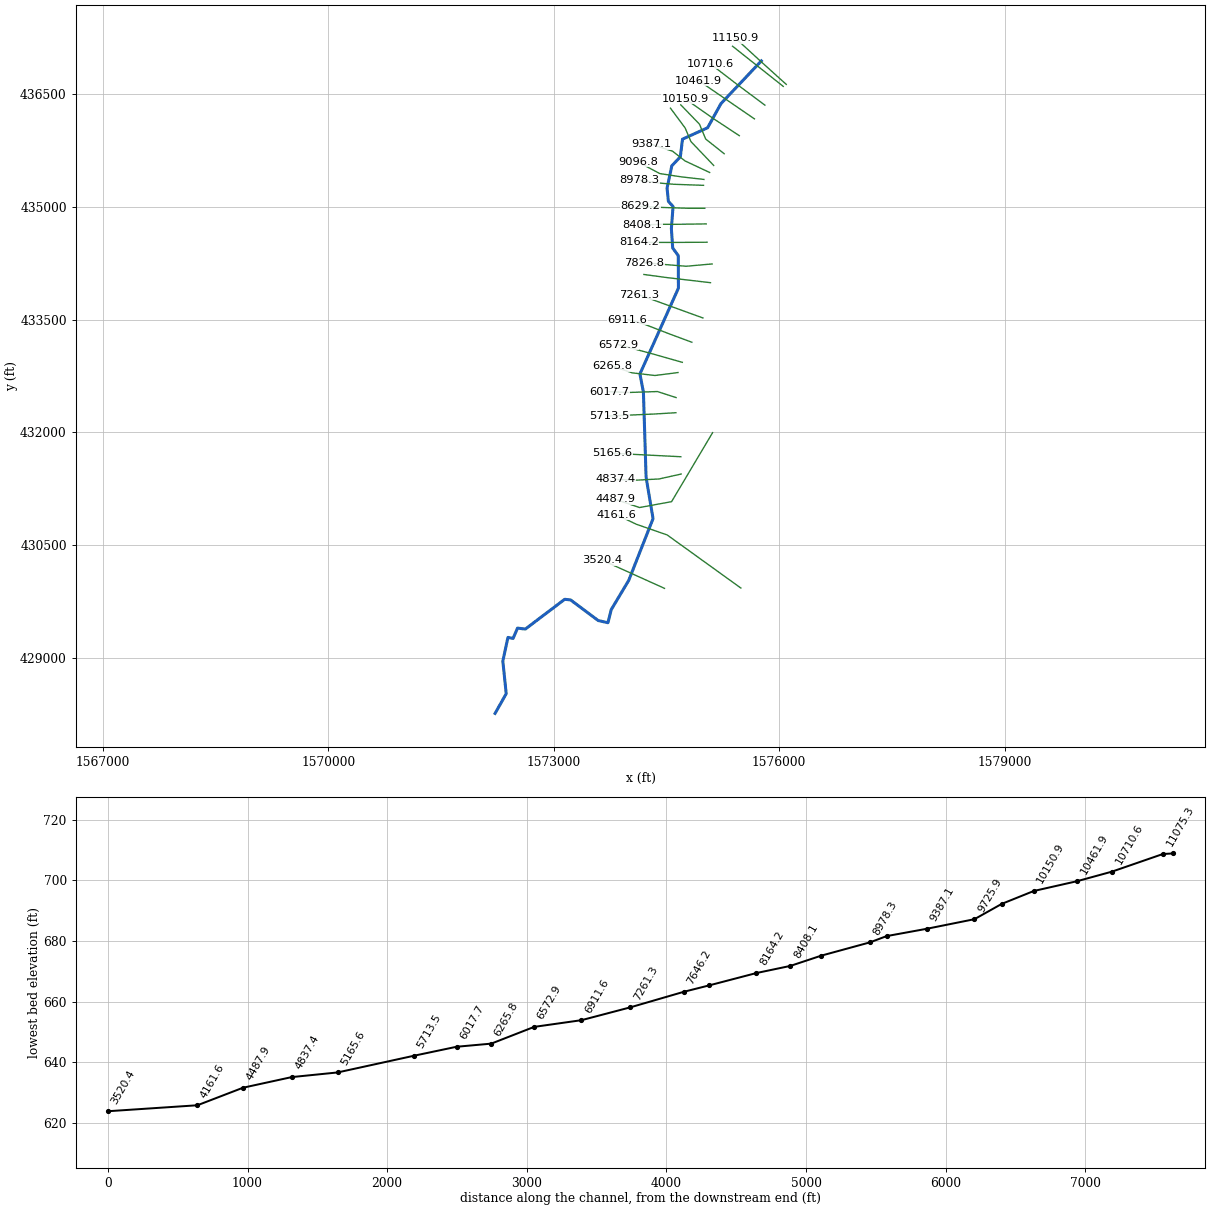
--- LTLELYNCR.prj (project) ---

Proj Title=LTLELYNCR
Current Plan=p01
Default Exp/Contr=0,0
English Units
Geom File=g01
Flow File=f01
Plan File=p01
BEGIN DESCRIPTION:
END DESCRIPTION:
DSS Export Rating Curves= 0
DSS Export Rating Curve Sorted= 0
DSS Export Volume Flow Curves= 0
DXF OffsetX= 0
DXF OffsetY= 0
DXF ScaleX= 0
DXF ScaleY= 0

--- LTLELYNCR.p01 (plan) ---

Plan Title=Floodplain
Program Version=4.00
Geom File=g01
Flow File=f01
K Sum by GR=0
Std Step Tol=0.01
Critical Tol=0.01
Num of Std Step Trials=20
Max Error Tol=0.3
Flow Tol Ratio=0.001
Split Flow NTrial=30
Split Flow Tol=0.02
Split Flow Ratio=0.02
Log Output Level=0
Friction Slope Method=1
Unsteady Friction Slope Method=2
Unsteady Bridges Friction Slope Method=1
Global Log Level=0
CheckData=False
Run HTab=0
Run UNet=0
Run PostProcess=0
UNET Theta=0
UNET Theta Warmup=0
UNET ZTol=0
UNET ZSATol=0
UNET MxIter=0
UNET MaxInSteps=0
UNET DtIC=0
UNET DtMin=0
UNET MaxCRTS=0
UNET WFStab=0
UNET SFStab=0
UNET WFX=0
UNET SFX=0
UNET DSS MLevel=0
UNET DZMax Abort=0
UNET Convert EG Bridges=0
UNET Use Existing IB Tables=0
UNET Froude Limit=0
UNET Froude Power=0
Write IC File=0
Echo Input=False
Echo Output=False
Write Detailed=0

--- LTLELYNCR.f01 (steady flow) ---

Flow Title=NFF Regression Equation
Program Version=4.00
Number of Profiles=1
Profile Names=P100yr
River Rch & RM=LTLELYNCR,Main      ,11150.9
     333
River Rch & RM=LTLELYNCR,Main      ,11075.3
     430
River Rch & RM=LTLELYNCR,Main      ,10461.9
     464
River Rch & RM=LTLELYNCR,Main      ,8978.3
     515
River Rch & RM=LTLELYNCR,Main      ,6572.9
     545
River Rch & RM=LTLELYNCR,Main      ,6265.8
     618
River Rch & RM=LTLELYNCR,Main      ,4487.9
     657
River Rch & RM=LTLELYNCR,Main      ,4161.6
    1007
Boundary for River Rch & Prof#=LTLELYNCR,Main      ,1
Up Type=0
Dn Type=3
Dn Slope=0.010277

--- LTLELYNCR.g01 (geometry) ---

Geom Title=USGS 10m DEM
Program Version=4.00

River Reach=LTLELYNCR       ,Main
Reach XY= 30
     1575762.286      436942.472     1575224.657      436374.202
     1575047.407      436053.229     1574713.277      435901.284
     1574684.222      435666.666     1574570.853      435546.789
     1574507.687      435250.709     1574525.129      435074.684
     1574587.517      435005.384     1574564.995        434710.9
     1574582.625      434453.064     1574656.639      434351.967
     1574658.814      433918.959     1574146.785      432777.732
     1574193.017      432534.735     1574228.576      431404.517
     1574321.079      430852.282     1573997.651      430031.026
     1573765.011       429641.75     1573721.031      429467.674
     1573591.813      429496.696     1573223.427      429771.334
     1573145.491      429779.189     1572621.667      429382.948
     1572517.855      429396.151     1572458.744      429258.505
     1572390.656      429272.399     1572322.542      428957.228
      1572367.52      428523.409     1572219.493      428261.541

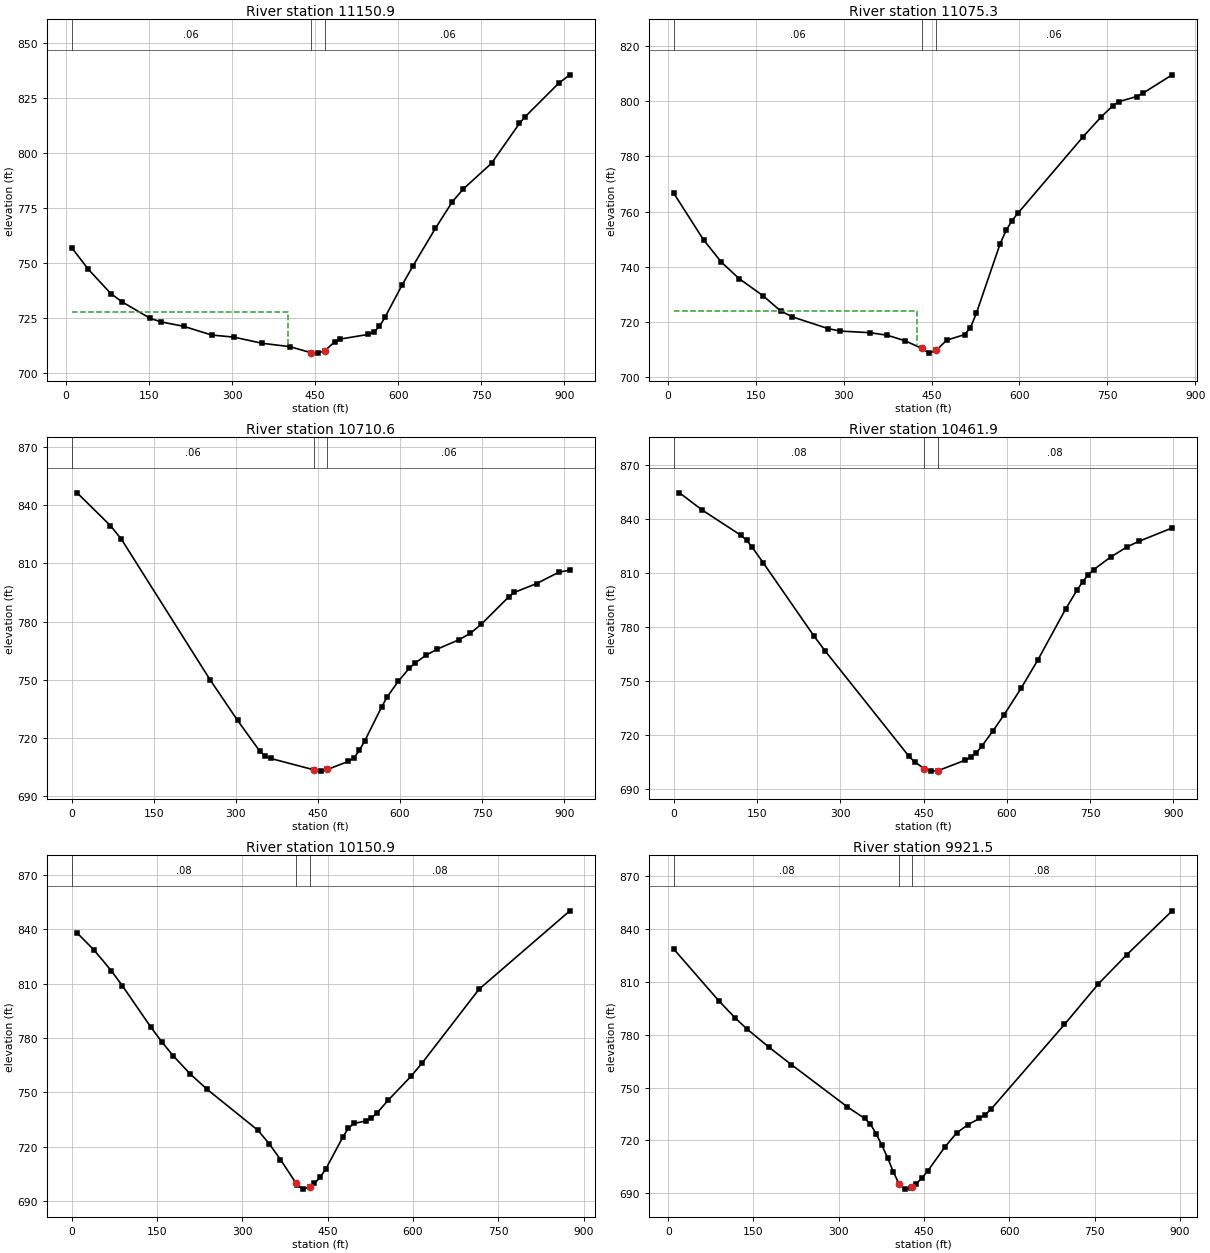
Type RM Length L Ch R = 1 ,11150.9 ,73.8,75.7,77.8
XS GIS Cut Line= 3
     1576093.441       436630.29     1575755.588      436935.046
     1575420.502      437242.882
#Sta/Elev= 30
    10.1  756.96    40.4  747.03    80.9  736.04   101.1  732.27   151.7  724.79
   171.9  723.12   212.3  721.15   262.9  717.17   303.3   716.2   353.9  713.42
   404.4  711.87   442.5  709.13     455  708.93   467.5  710.02   485.3  714.06
   495.4  715.33     546  717.44   556.1  718.49   566.2  721.11   576.3   725.3
   606.7  739.76   626.9  748.68   667.3  765.72   697.7  777.74   717.9  783.67
   768.5  795.26     819  813.41   829.1  816.39   889.8  831.66     910  835.49
#Mann= 3 , 0 , 0
    10.1     .06       0   442.5    .045       0   467.5     .06       0
#XS Ineff= 2 , 0
           400.4  727.63
Permanent Ineff=
       F       F
Bank Sta=442.5,467.5
XS Rating Curve= 0 ,0
Exp/Cntr=0.3,0.1

Type RM Length L Ch R = 1 ,11075.3 ,364,364.7,365
XS GIS Cut Line= 2
     1576053.564       436603.53      1575378.92      437137.989
#Sta/Elev= 30
    10.1  766.58    60.8  749.75    91.1  741.71   121.5  735.71     162  729.57
   192.4     724   212.6  721.84   273.4  717.62   293.6  716.73   344.3  716.14
   374.7  715.21     405  713.18     433  710.49  445.54  708.73     458  709.75
   475.9  713.42   506.3  715.44   516.4  717.93   526.5  723.18     567  748.31
   577.2  753.16   587.3  756.72   597.4   759.4   708.8  787.14   739.2  794.23
   759.4  798.32   769.6  799.82   799.9  801.67   810.1  802.78   860.7  809.54
#Mann= 3 , 0 , 0
    10.1     .06       0     433    .045       0     458     .06       0
#XS Ineff= 2 , 0
          424.63  723.91
Permanent Ineff=
       F       F
Bank Sta=433,458
XS Rating Curve= 0 ,0
Exp/Cntr=0.3,0.1

Type RM Length L Ch R = 1 ,10710.6 ,247.5,248.7,250.2
XS GIS Cut Line= 3
     1575809.325      436354.035     1575444.563      436625.903
     1575083.521      436903.178
#Sta/Elev= 30
    10.1  846.29    70.8  829.43      91   822.4   252.7   750.1   303.3  729.01
   343.7  713.25   353.8  710.62   363.9  709.43   442.4  703.61   454.9  702.92
   467.4  703.78   505.5  707.93   515.6  709.72   525.7  713.58   535.9  718.68
   566.2  735.88   576.3  741.07   596.6  749.14   616.8  755.89   626.9   758.5
   647.1  762.53   667.4  765.71   707.8  770.62   728.1  773.86   748.3  778.54
   798.9  792.78     809  795.01   849.5  799.54   889.9  805.38   910.2  806.49
#Mann= 3 , 0 , 0
       0     .06       0   442.4    .045       0   467.4     .06       0
Bank Sta=442.4,467.4
XS Rating Curve= 0 ,0
Exp/Cntr=0.3,0.1

Type RM Length L Ch R = 1 ,10461.9 ,310.5,311,310.5
XS GIS Cut Line= 2
     1575670.242      436171.143     1574929.886      436679.316
#Sta/Elev= 30
    10.1  854.67    50.4  845.23   121.1  830.99   131.2  828.22   141.3  824.31
   161.4  815.58   252.2  775.08   272.4  766.77   423.8  707.99   433.9  704.93
   451.6  701.09   464.1  699.78   476.6  700.09   524.7  705.83   534.8  707.38
   544.8  709.86   554.9  713.66   575.1  722.18   595.3  731.24   625.6   745.8
   655.8  761.57   706.3  790.12   726.5  800.46   736.5  805.07   746.6     809
   756.7  811.94     787  818.89   817.3  824.66   837.4   827.6     898  835.11
#Mann= 3 , 0 , 0
       0     .08       0   451.6    .045       0   476.6     .08       0
Bank Sta=451.6,476.6
XS Rating Curve= 0 ,0
Exp/Cntr=0.3,0.1

Type RM Length L Ch R = 1 ,10150.9 ,245.9,229.4,213.9
XS GIS Cut Line= 3
     1575468.725      435947.722     1575129.042      436171.778
     1574744.899      436440.638
#Sta/Elev= 30
     9.9  837.95    39.7  828.48    69.5  817.24    89.3  808.84   138.9  786.17
   158.8  777.75   178.6  770.17   208.4  760.17   238.2  751.65   327.5  729.05
   347.4  721.59   367.2  712.83   394.4  699.88     397  698.67   406.9  696.54
   419.4  697.96   426.9   699.7   436.9  703.12   446.8  707.66   476.8  725.26
   486.7  730.31   496.7  732.82   516.7  734.16   526.6  735.75   536.6  738.49
   556.6  745.68   596.5   758.8   616.4  766.26   716.2  806.93   875.8  850.21
#Mann= 3 , 0 , 0
       0     .08       0   394.4    .045       0   419.4     .08       0
Bank Sta=394.4,419.4
XS Rating Curve= 0 ,0
Exp/Cntr=0.3,0.1

Type RM Length L Ch R = 1 ,9921.5  ,195.4,195.6,195.7
XS GIS Cut Line= 4
     1575267.559      435707.653     1575020.832      435903.914
     1574939.524      436100.174     1574689.993      436358.115
#Sta/Elev= 30
     9.9  828.58    88.7  799.35   118.2  789.38   137.9  783.43   177.3  772.89
   216.7  762.99   315.3  738.98   345.6  732.45   355.7  729.22   365.8  723.76
     376  717.15   386.1  710.03   396.2  701.96   406.3  695.11   416.4  692.29
   426.5  692.94   428.9  693.53   436.7  695.45   446.8  698.76   456.9  702.77
   487.2   716.4   507.5  724.22   527.7  728.99   547.6  732.41   557.6  734.55
   567.6  737.55   697.2  785.85     757  808.93   806.8  825.43   886.6  850.37
#Mann= 3 , 0 , 0
     9.9     .08       0   406.3    .045       0   428.9     .08       0
Bank Sta=406.3,428.9
XS Rating Curve= 0 ,0
Exp/Cntr=0.3,0.1

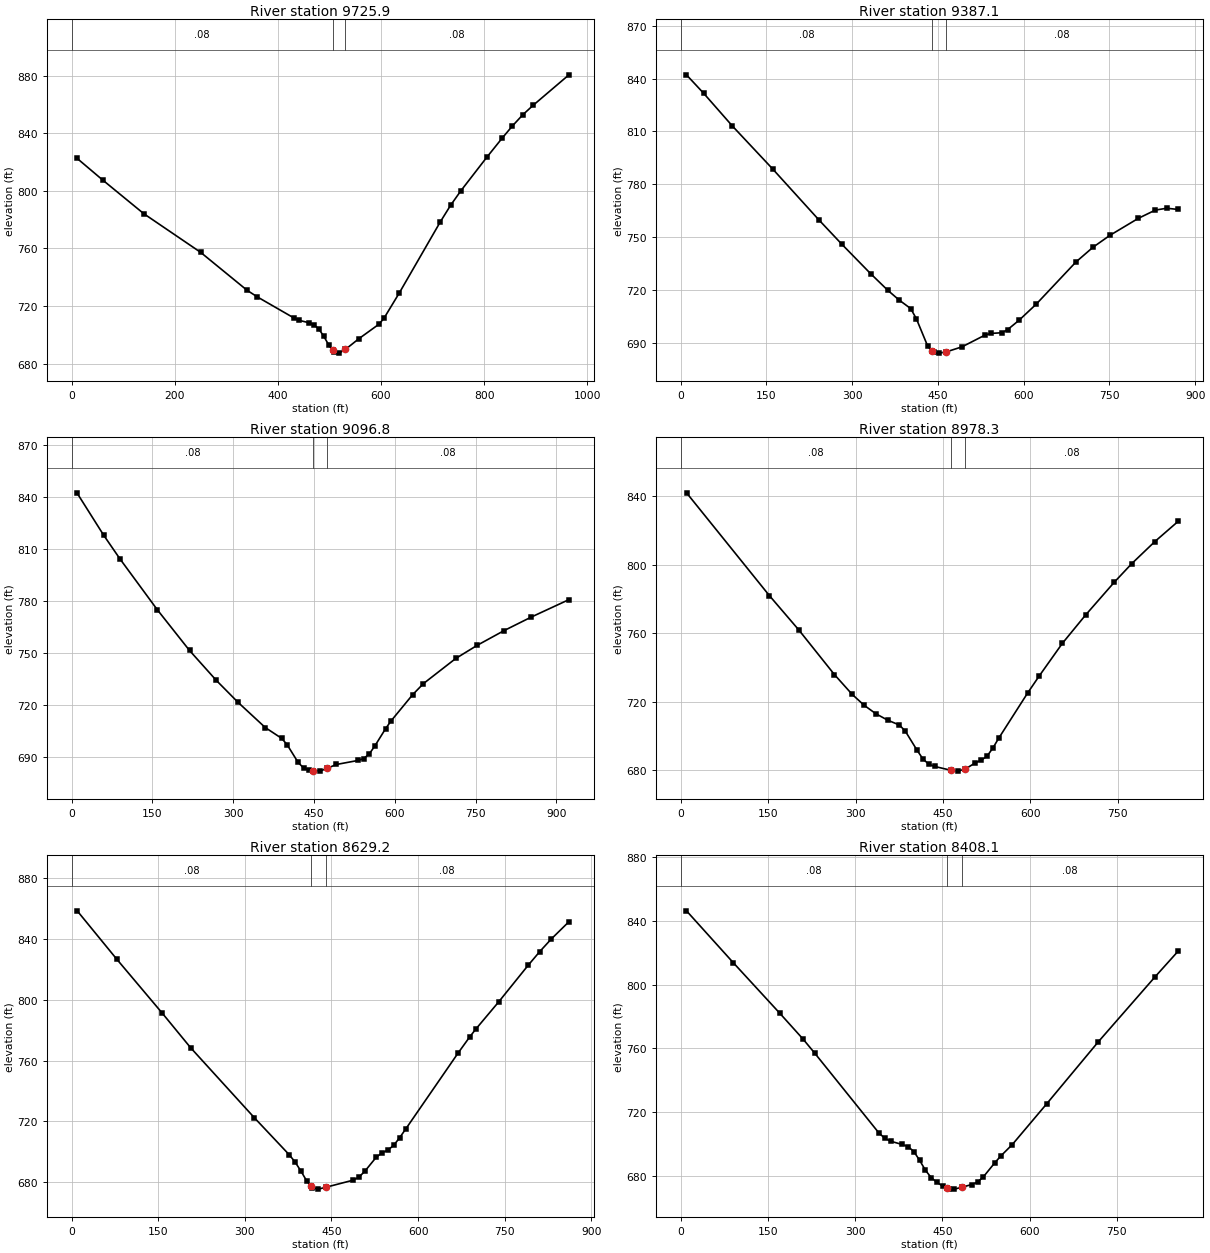
Type RM Length L Ch R = 1 ,9725.9  ,324.7,338.8,352.4
XS GIS Cut Line= 4
     1575128.436      435551.328     1574824.551      435870.119
     1574748.871      436049.707     1574552.822      436313.764
#Sta/Elev= 30
      10   822.7    60.1  807.52   140.1  784.04   250.2  757.24   340.3  730.87
   360.3  726.25   430.4  711.79   440.4  710.07   459.9  708.37   469.7  707.02
   479.4  703.97   489.1  698.87   498.9  692.71   505.9  689.36   508.6  688.06
   518.4  687.24   530.9  689.82   557.4  697.36   596.3  707.41   606.1  711.71
   635.3  728.99     715  778.46     735  789.99   754.9  800.05   804.7   823.1
   834.6  836.44   854.6  844.97   874.5  852.65   894.4  859.18   964.2  880.47
#Mann= 3 , 0 , 0
       0     .08       0   505.9    .045       0   530.9     .08       0
Bank Sta=505.9,530.9
XS Rating Curve= 0 ,0
Exp/Cntr=0.3,0.1

Type RM Length L Ch R = 1 ,9387.1  ,276.3,290.4,305
XS GIS Cut Line= 4
     1575074.102      435458.123     1574746.068      435612.327
     1574580.648      435741.298     1574297.473      435833.821
#Sta/Elev= 30
    10.1  842.12    40.3  831.62    90.6  813.02   161.1  788.62   241.6  759.83
   281.9  745.95   332.3  729.22   362.5  719.73   382.4  714.19   402.4   709.4
   412.4  703.58   432.4  687.87   439.9  685.33   442.4  684.48   452.4   684.1
   464.9  684.83   492.3  687.69   532.3  694.33   542.3  695.28   562.2  695.68
   572.2   697.5   592.1   702.8   621.9  711.87   691.4  735.82   721.2  744.19
     751     751   800.6  760.63   830.4  765.32   850.3  766.37   870.1  765.68
#Mann= 3 , 0 , 0
       0     .08       0   439.9    .045       0   464.9     .08       0
Bank Sta=439.9,464.9
XS Rating Curve= 0 ,0
Exp/Cntr=0.3,0.1

Type RM Length L Ch R = 1 ,9096.8  ,116.6,118.4,120.3
XS GIS Cut Line= 4
     1574998.402        435365.6     1574701.605      435399.197
     1574410.532      435443.776     1574119.222      435599.119
#Sta/Elev= 30
      10  842.18    59.7  817.72    89.6   804.2   159.3  774.71     219  751.25
   268.8  733.98   308.8  721.42   359.6   706.8   390.1  700.56   400.2  696.89
   420.5  686.74   430.7  683.47   440.8  682.29   448.7  681.88   461.2  681.66
   473.7  683.18   491.6  685.49   532.2  687.84   542.4  688.92   552.5  691.52
   562.7  696.02     583  706.16   593.2  710.66   633.2  725.76   653.2  732.14
   713.2  746.64   753.2  754.26   803.2  762.76   853.3  770.51   923.3  780.58
#Mann= 3 , 0 , 0
       0     .08       0   448.7    .045       0   473.7     .08       0
Bank Sta=448.7,473.7
XS Rating Curve= 0 ,0
Exp/Cntr=0.3,0.1

Type RM Length L Ch R = 1 ,8978.3  ,347.8,349.2,350.6
XS GIS Cut Line= 4
     1574992.794      435287.096     1574597.471      435301.115
     1574398.407      435317.937     1574143.269      435354.385
#Sta/Elev= 30
    10.1  841.83   152.1  781.95   202.9   761.8   263.7  735.91   294.1  724.37
   314.4  718.08   334.7  713.08     355  709.33   375.3  706.47   385.4  702.86
   405.6  691.71   415.5  686.73   425.5  683.64   435.5  682.35     463  680.15
   475.5  679.61     488   680.8   505.4  684.43   515.4  685.99   525.4  688.29
   535.4  693.02   545.4  698.73   595.3  725.25   615.2  735.19   654.8  754.15
   694.5   770.6     744  789.83   773.8  800.59   813.4  813.45   853.1  825.15
#Mann= 3 , 0 , 0
       0     .08       0     463    .045       0     488     .08       0
Bank Sta=463,488
XS Rating Curve= 0 ,0
Exp/Cntr=0.3,0.1

Type RM Length L Ch R = 1 ,8629.2  ,220.2,221.1,222
XS GIS Cut Line= 4
     1575009.617      434981.491     1574793.731      434981.491
     1574451.677      434992.706     1574148.876      435006.724
#Sta/Elev= 30
     9.8  858.67    78.5   826.7     157  791.25   206.1  768.47   316.5  722.29
   376.9  697.89     387  693.12   397.1  687.17   407.1  680.68   414.8  677.19
   417.2  676.11   427.3  675.22   439.8   676.4   487.7  681.14   497.7  683.17
   507.8  686.99   527.9  696.41     538  699.21   548.1  701.02   558.1  704.22
   568.2  709.19   578.3  714.68   669.3  764.94   689.5  775.61   699.6  780.53
     740  798.85   790.5  822.72   810.7  831.82   830.9   840.2   861.2  851.49
#Mann= 3 , 0 , 0
       0     .08       0   414.8    .045       0   439.8     .08       0
Bank Sta=414.8,439.8
XS Rating Curve= 0 ,0
Exp/Cntr=0.3,0.1

Type RM Length L Ch R = 1 ,8408.1  ,243.7,243.9,243.8
XS GIS Cut Line= 4
     1575029.243      434774.016     1574628.311      434768.409
     1574429.248      434768.409     1574174.109      434759.997
#Sta/Elev= 30
      10  846.19    90.2  813.81   170.4  782.05   210.5  765.83   230.6     757
   340.8  707.07   350.8  703.76   360.9  701.88   380.9   699.8   390.9  698.52
     401  695.39   410.9  689.89   420.9  683.69   430.8  679.04   440.8  676.07
   450.7  673.68   458.1  672.46   460.7  672.03   470.6  671.84   483.1  672.97
   500.5  674.72   510.5  676.25   520.4  679.48   540.3  688.39   550.3  692.53
   570.2  699.73   629.5  725.32   717.9  764.02     816  804.94   855.3  820.86
#Mann= 3 , 0 , 0
       0     .08       0   458.1    .045       0   483.1     .08       0
Bank Sta=458.1,483.1
XS Rating Curve= 0 ,0
Exp/Cntr=0.3,0.1

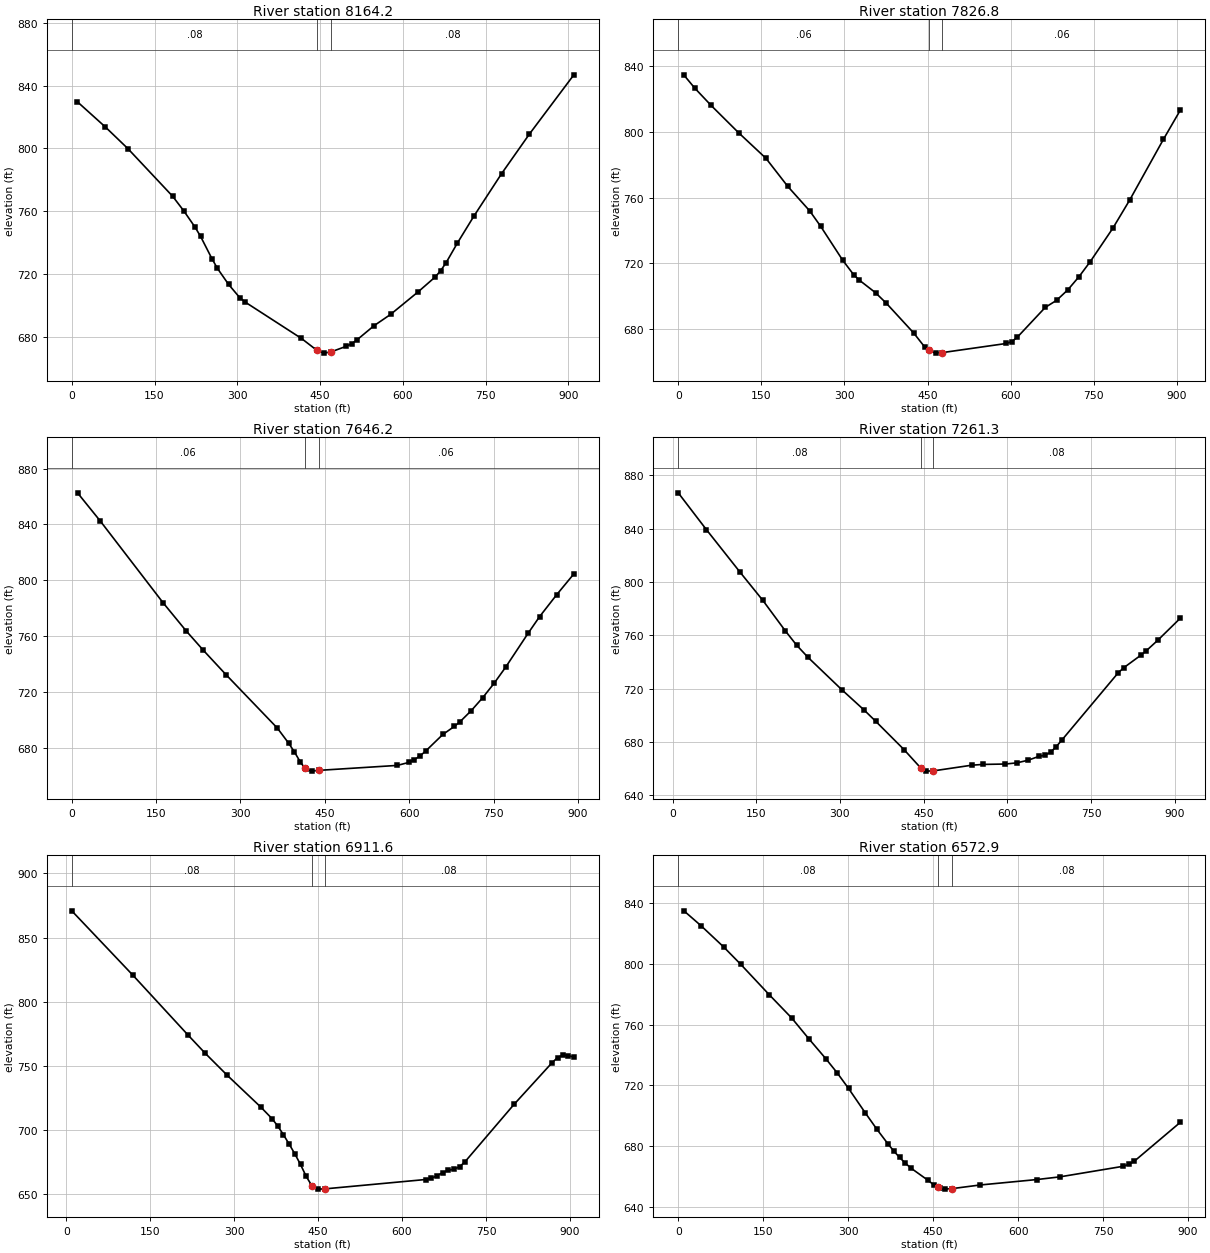
Type RM Length L Ch R = 1 ,8164.2  ,339.8,337.4,335.3
XS GIS Cut Line= 3
     1575040.458      434530.093     1574583.522      434527.215
     1574130.592      434528.288
#Sta/Elev= 30
    10.2  829.62    60.9  813.57   101.5  799.85   182.8  769.43   203.1  760.08
   223.4  749.75   233.5  743.81   253.9  729.73     264  723.45   284.3  713.21
   304.6  704.76   314.8  701.88   416.3  678.82   444.4  671.22   456.9  669.48
   469.4  670.22   497.2   673.8   507.3  675.48   517.3  678.05   547.5  686.88
   577.7  694.13   628.1  708.64   658.2  717.87   668.3  721.89   678.4   727.1
   698.5  739.42   728.7  756.74     779  783.87   829.4  809.08   909.9  846.81
#Mann= 3 , 0 , 0
       0     .08       0   444.4    .045       0   469.4     .08       0
Bank Sta=444.4,469.4
XS Rating Curve= 0 ,0
Exp/Cntr=0.3,0.1

Type RM Length L Ch R = 1 ,7826.8  ,181.5,180.5,179.6
XS GIS Cut Line= 4
     1575107.747       434241.31      1574762.89      434210.469
     1574488.126      434232.899      1574204.95      434258.132
#Sta/Elev= 30
     9.9  834.62    29.7  826.58    59.4  815.99   108.8  799.46   158.3  783.87
   197.8  766.75   237.4  751.86   257.2  742.45   296.8  721.92   316.6  713.11
   326.4  709.91   356.1  702.14   375.8  695.68     425  677.65   444.7  669.21
   451.9   667.1   464.4  665.42   476.9  665.75   592.4   671.3   602.2  672.47
   612.1  675.13   662.5  693.24   682.8  697.49   703.1  703.87   723.4  711.92
   743.8  721.12   784.4  741.35   814.8  758.47   875.7  795.39   906.2  813.14
#Mann= 3 , 0 , 0
       0     .06       0   451.9    .045       0   476.9     .06       0
Bank Sta=451.9,476.9
XS Rating Curve= 0 ,0
Exp/Cntr=0.3,0.1

Type RM Length L Ch R = 1 ,7646.2  ,391.4,385,378.5
XS GIS Cut Line= 3
     1575085.317      433991.779     1574510.555      434059.069
     1574199.343      434101.124
#Sta/Elev= 30
    10.2  862.61    50.8  842.36   162.4  783.87     203  763.93   233.5  750.05
   274.1  732.45   365.5  694.15   385.8  683.22   395.9  677.05   406.1  670.03
   413.9  665.76   416.2   664.5   426.4  663.32   438.9  663.86   578.7  667.41
   598.9  669.51   609.1  671.48   619.2  674.21   629.3  677.72   659.7  689.55
     680  695.28   690.1   698.6   710.4  706.68   730.6  715.89   750.9  726.21
   771.2  737.61   811.7  762.23   831.9  774.02   862.3  789.71   892.7  804.54
#Mann= 3 , 0 , 0
       0     .06       0   413.9    .045       0   438.9     .06       0
Bank Sta=413.9,438.9
XS Rating Curve= 0 ,0
Exp/Cntr=0.3,0.1

Type RM Length L Ch R = 1 ,7261.3  ,350.2,349.6,349
XS GIS Cut Line= 3
     1574985.473      433522.291     1574557.708      433677.348
     1574129.943      433832.404
#Sta/Elev= 30
    10.1   866.8    60.7  839.14   121.3   807.1   161.8  786.14   202.2  763.23
   222.4  752.55   242.7  743.46   303.3  719.19   343.8  703.76     364  695.55
   414.6  674.38   444.9  660.47     455  658.17   467.5  658.36   535.9   662.6
   556.1  663.19   596.6   663.5   616.8  664.35     637  666.33   657.2  669.32
   667.3  670.03   677.4  672.34   687.6  676.53   697.7  681.46   798.8  731.94
   808.9  735.76   839.2  745.06   849.3  748.52   869.6  756.27     910  772.81
#Mann= 3 , 0 , 0
    10.1     .08       0   444.9    .045       0   467.5     .08       0
Bank Sta=444.9,467.5
XS Rating Curve= 0 ,0
Exp/Cntr=0.3,0.1

Type RM Length L Ch R = 1 ,6911.6  ,335.8,338.7,341.7
XS GIS Cut Line= 4
     1574837.714      433199.379     1574531.057       433313.28
     1574180.593      433449.085     1573983.457      433501.655
#Sta/Elev= 30
     9.9  870.83     119   820.7   218.1  773.81   247.8  760.05   287.5  742.74
   347.4  717.99   367.8  708.84   377.9  703.12   388.1  696.37   398.2  689.09
   408.4  681.48   418.6  673.16   428.7   663.9   438.9  656.58     449  653.94
   461.5  654.11     642  661.43   652.2  662.37   662.4  664.35   672.5  666.82
   682.7  668.61   692.8  669.48     703  671.44   712.7  675.36   800.1  719.96
   868.1  752.47   877.9  756.48   887.6   758.4   897.3  758.02     907  756.78
#Mann= 3 , 0 , 0
     9.9     .08       0   438.9    .045       0   461.5     .08       0
Bank Sta=438.9,461.5
XS Rating Curve= 0 ,0
Exp/Cntr=0.3,0.1

Type RM Length L Ch R = 1 ,6572.9  ,302.9,307.1,311.4
XS GIS Cut Line= 3
     1574710.671       432932.15      1574325.16       433041.67
     1573856.413      433168.713
#Sta/Elev= 30
      10  834.92    40.1  825.16    80.2  811.14   110.2  799.76   160.3  779.84
   200.4  764.33   230.4  750.77   260.5  737.61   280.5  728.32   300.6  718.05
   330.6  701.73   350.7  691.14   370.7  681.29   380.7  676.76   390.7   672.6
   400.8  668.84   410.9  665.55   441.2  657.47   451.4  654.46   459.1  652.84
   461.5  652.34   471.6  651.73   484.1  652.09   532.3  654.43   633.5  658.05
   673.9  659.81   785.2  666.74   795.4  668.03   805.5  670.21   886.4   695.7
#Mann= 3 , 0 , 0
       0     .08       0   459.1    .045       0   484.1     .08       0
Bank Sta=459.1,484.1
XS Rating Curve= 0 ,0
Exp/Cntr=0.3,0.1

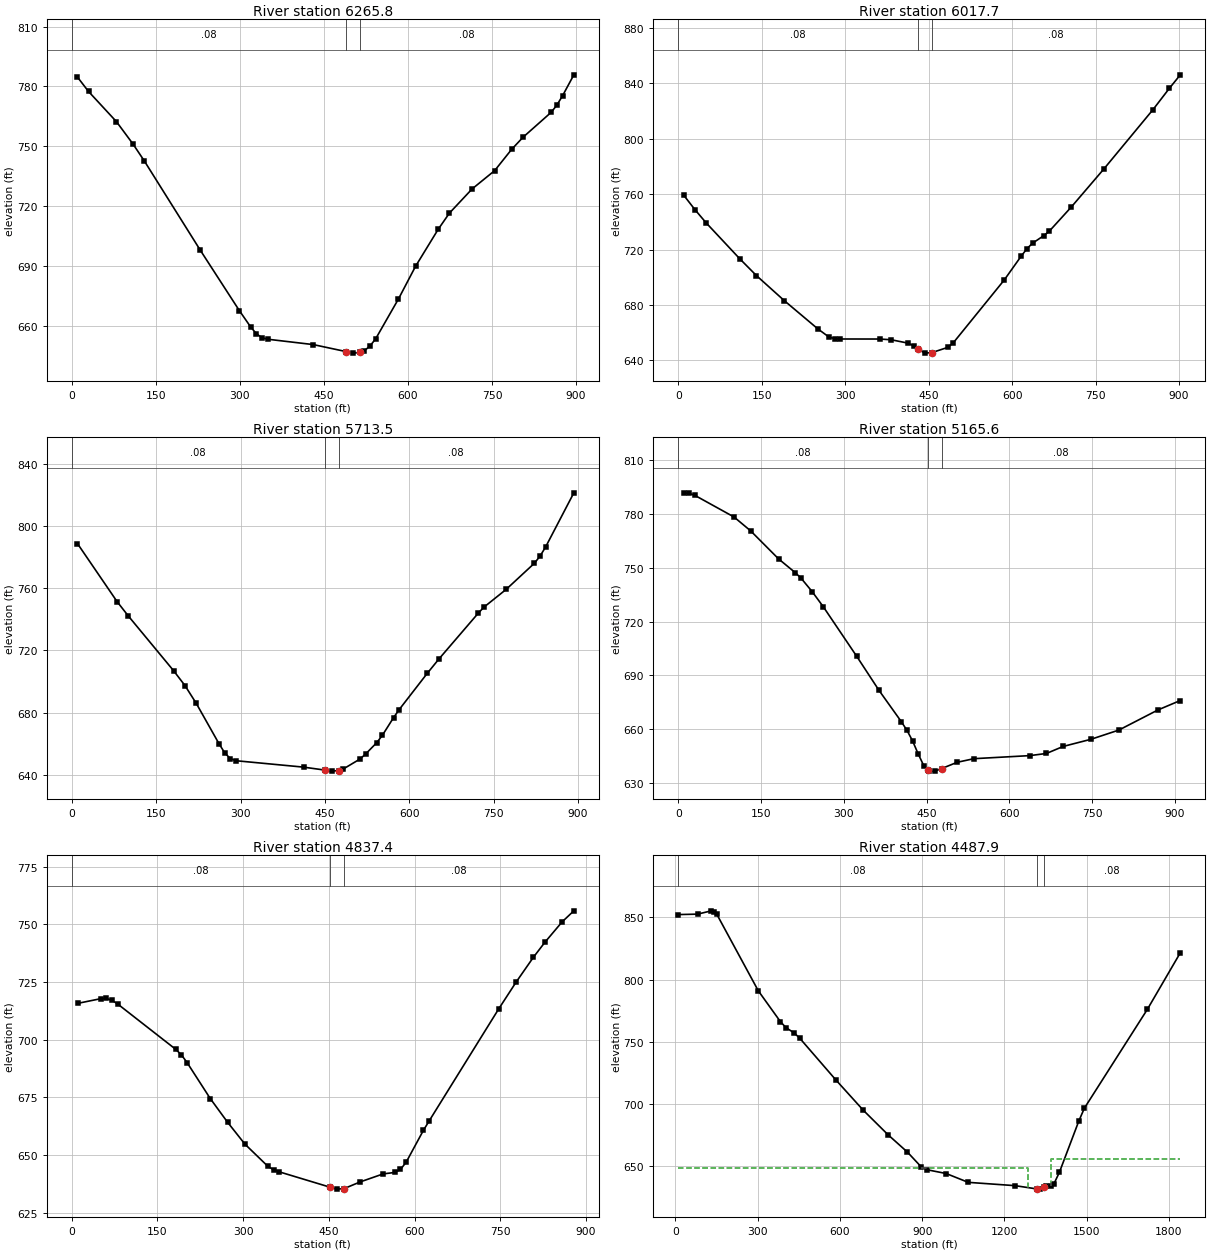
Type RM Length L Ch R = 1 ,6265.8  ,243.8,248.1,252.4
XS GIS Cut Line= 4
      1574653.72      432796.345     1574347.064      432756.918
     1574044.788      432791.964     1573777.559      432883.961
#Sta/Elev= 30
      10  784.75    29.9  777.49    79.8  762.32   109.7  750.96   129.7  742.54
   229.4  697.84   299.2   667.5   319.3  659.33   329.5  655.94   339.6  653.91
   349.8  653.18   430.9   650.5   489.4  646.99   501.9  646.21   514.4  646.55
   522.2  647.38   532.3  649.81   542.5  653.45   583.1  673.41   613.5  689.73
   653.9   708.3     674  716.45   714.4  728.56   754.8  737.79   785.1  748.45
   805.3  754.49   855.7  767.04   865.8  770.65   875.9  775.31   896.1  785.84
#Mann= 3 , 0 , 0
       0     .08       0   489.4    .045       0   514.4     .08       0
Bank Sta=489.4,514.4
XS Rating Curve= 0 ,0
Exp/Cntr=0.3,0.1

Type RM Length L Ch R = 1 ,6017.7  ,303.9,304.2,304.5
XS GIS Cut Line= 4
     1574627.435      432463.404     1574379.065      432543.535
     1573983.101      432530.424     1573738.132      432542.258
#Sta/Elev= 30
      10  759.17    30.1  748.77    50.2  739.26   110.4   713.4   140.5  701.21
   190.7  683.06   250.9   662.7   271.1  656.74   281.3  655.66   291.5  655.39
   362.6  655.36   382.9  654.83   413.4  652.37   423.5   650.3   431.3  647.81
   443.8  645.18   456.3  645.61   484.5  649.34   494.6  652.75     586  698.04
   616.5  715.29   626.7  720.58   636.8  724.57   657.2  730.08     667  733.29
   706.2  750.59   765.1  778.24   853.4  821.11   882.8  836.48   902.4  846.19
#Mann= 3 , 0 , 0
       0     .08       0   431.3    .045       0   456.3     .08       0
Bank Sta=431.3,456.3
XS Rating Curve= 0 ,0
Exp/Cntr=0.3,0.1

Type RM Length L Ch R = 1 ,5713.5  ,550.8,547.9,545.1
XS GIS Cut Line= 3
     1574625.293      432261.649     1574333.921      432244.363
     1573733.751      432218.079
#Sta/Elev= 30
    10.1  788.91    80.5  751.53   100.6   742.2   181.2  706.89   201.3  697.36
   221.4  685.86   261.7  659.93   271.8  654.08   281.8   650.3   291.9  648.94
     412  644.81   449.6  642.92   462.1  642.23   474.6   642.6   482.1  643.48
   512.2  649.98   522.2  653.18   542.2  660.59   552.2  665.32   572.2  676.78
   582.2  681.95   632.3  705.41   652.3  714.33   722.4  743.93   732.4  747.81
   772.5  759.45   822.5  776.24   832.6  780.86   842.6  786.85   892.6  821.62
#Mann= 3 , 0 , 0
       0     .08       0   449.6    .045       0   474.6     .08       0
Bank Sta=449.6,474.6
XS Rating Curve= 0 ,0
Exp/Cntr=0.3,0.1

Type RM Length L Ch R = 1 ,5165.6  ,325.4,328.2,331
XS GIS Cut Line= 3
     1574690.874      431676.118     1574236.452      431699.038
      1573782.03      431721.959
#Sta/Elev= 30
    10.1  791.65    20.2  791.34    30.3  790.21   101.1   778.2   131.4  770.43
     182  754.83   212.3  747.16   222.4   744.2   242.7  736.66   262.9  728.23
   323.6  700.58     364  681.62   404.4  664.22   414.6   659.4   424.7  653.56
   434.8  646.36   444.9  639.82   452.6  637.53     455  636.82   465.1  636.71
   477.6  638.17   505.6  641.63   535.9  643.64     637  645.34   667.3  646.54
   697.7  650.46   748.2  654.45   798.8  659.59   869.6  670.79     910  676.03
#Mann= 3 , 0 , 0
       0     .08       0   452.6    .045       0   477.6     .08       0
Bank Sta=452.6,477.6
XS Rating Curve= 0 ,0
Exp/Cntr=0.3,0.1

Type RM Length L Ch R = 1 ,4837.4  ,345.9,349.5,353
XS GIS Cut Line= 4
     1574695.338      431445.961     1574399.633      431380.249
     1574087.501      431363.821     1573824.653      431374.773
#Sta/Elev= 30
    10.1  715.71    50.5  717.75    60.6  717.86    70.7  717.01    80.8  715.36
   181.8  695.82   191.8  693.42   201.9  690.01   242.3  674.47   272.6   664.2
   302.9  654.72   343.2  645.06   353.3  643.57   363.4  642.65   451.7  636.04
   464.2  635.18   476.7  635.42   504.6   638.3   544.9  641.78   565.1  642.41
   575.2  643.71   585.2  646.87   615.5  660.74   625.6  664.83     747  713.28
   777.4  724.88   807.7  735.67     828  742.23   858.3  751.12   878.6  755.85
#Mann= 3 , 0 , 0
       0     .08       0   451.7    .045       0   476.7     .08       0
Bank Sta=451.7,476.7
XS Rating Curve= 0 ,0
Exp/Cntr=0.3,0.1

Type RM Length L Ch R = 1 ,4487.9  ,340.7,326.3,311.8
XS GIS Cut Line= 4
     1575113.568      431996.642     1574567.912      431078.439
     1574141.166      431000.214      1573819.31      431109.931
#Sta/Elev= 30
    10.1  852.23    80.6  852.58     131  855.24   141.1   854.5   151.1  852.36
   302.3  790.96   382.9  766.22   403.1  761.43   433.3   757.1   453.4  752.92
   584.4   719.6   685.2  695.06   775.9  675.29   846.4   661.4   896.8  649.51
     917  647.28   987.5  644.22  1068.1  637.12  1239.6  634.45  1317.9  631.85
  1330.4  631.67  1342.9  633.17  1350.6  634.01  1370.8  633.97  1380.9  635.93
  1401.1  645.34  1471.7  686.39  1491.9  696.67    1722  776.18    1842  821.55
#Mann= 3 , 0 , 0
    10.1     .08       0  1317.9    .045       0  1342.9     .08       0
#XS Ineff= 2 , 0
         1287.66  648.94 1369.11          655.79
Permanent Ineff=
       F       F
Bank Sta=1317.9,1342.9
XS Rating Curve= 0 ,0
Exp/Cntr=0.3,0.1

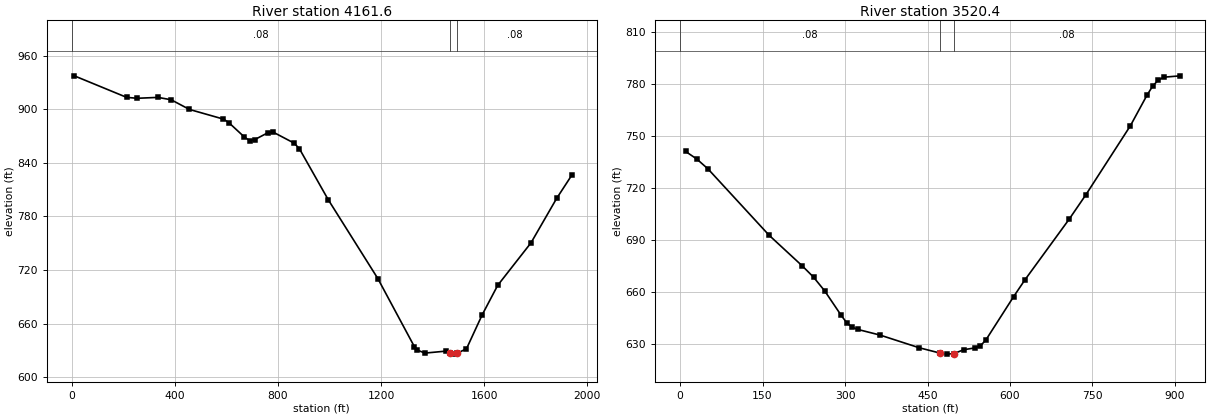
Type RM Length L Ch R = 1 ,4161.6  ,643.8,641.2,638.6
XS GIS Cut Line= 4
     1575489.359      429929.107     1574509.154      430635.512
     1574098.453      430777.889     1573829.642      430906.619
#Sta/Elev= 30
    10.2  937.48   213.2  913.37   253.8  912.34   335.1  913.33   385.8  910.68
   456.9  899.84   588.9  889.02   609.2  885.21   670.1  868.93   690.4  864.96
   710.7  866.17   761.5  873.79   781.8  874.42     863  862.12   883.3  855.95
     995  798.94  1187.9  710.43  1329.5  634.29  1339.6  630.65    1370  627.03
  1450.8  629.23  1468.7  627.29  1481.2  625.89  1493.7  626.68  1531.7  631.88
  1592.4  669.79  1652.8   702.9    1782  750.51  1881.3  800.16    1941  826.59
#Mann= 3 , 0 , 0
       0     .08       0  1468.7    .045       0  1493.7     .08       0
Bank Sta=1468.7,1493.7
XS Rating Curve= 0 ,0
Exp/Cntr=0.3,0.1

Type RM Length L Ch R = 1 ,3520.4  ,3524.5,3520.4,3504.4
XS GIS Cut Line= 3
     1574473.661      429924.944     1574059.028      430112.304
     1573644.394      430299.665
#Sta/Elev= 30
    10.1   740.9    30.3  736.56    50.6  730.88   161.8  692.57   222.4  674.79
   242.7  668.36   262.9  660.46   293.2  646.22   303.3  641.92   313.4  639.38
   323.6  638.14     364  634.89   434.8  627.61   472.8  624.52   485.3  623.92
   497.8  624.19   515.7  626.46   535.9  627.49     546  628.65   556.1  632.05
   606.7  657.14   626.9  666.66   707.8  701.87   738.1  715.93     819  755.73
   849.3  773.44   859.4  778.53   869.6  782.08   879.7  783.78     910  784.57
#Mann= 3 , 0 , 0
       0     .08       0   472.8    .045       0   497.8     .08       0
Bank Sta=472.8,497.8
XS Rating Curve= 0 ,0
Exp/Cntr=0.3,0.1

Chan Stop Cuts=-1
Use User Specified Reach Order=0